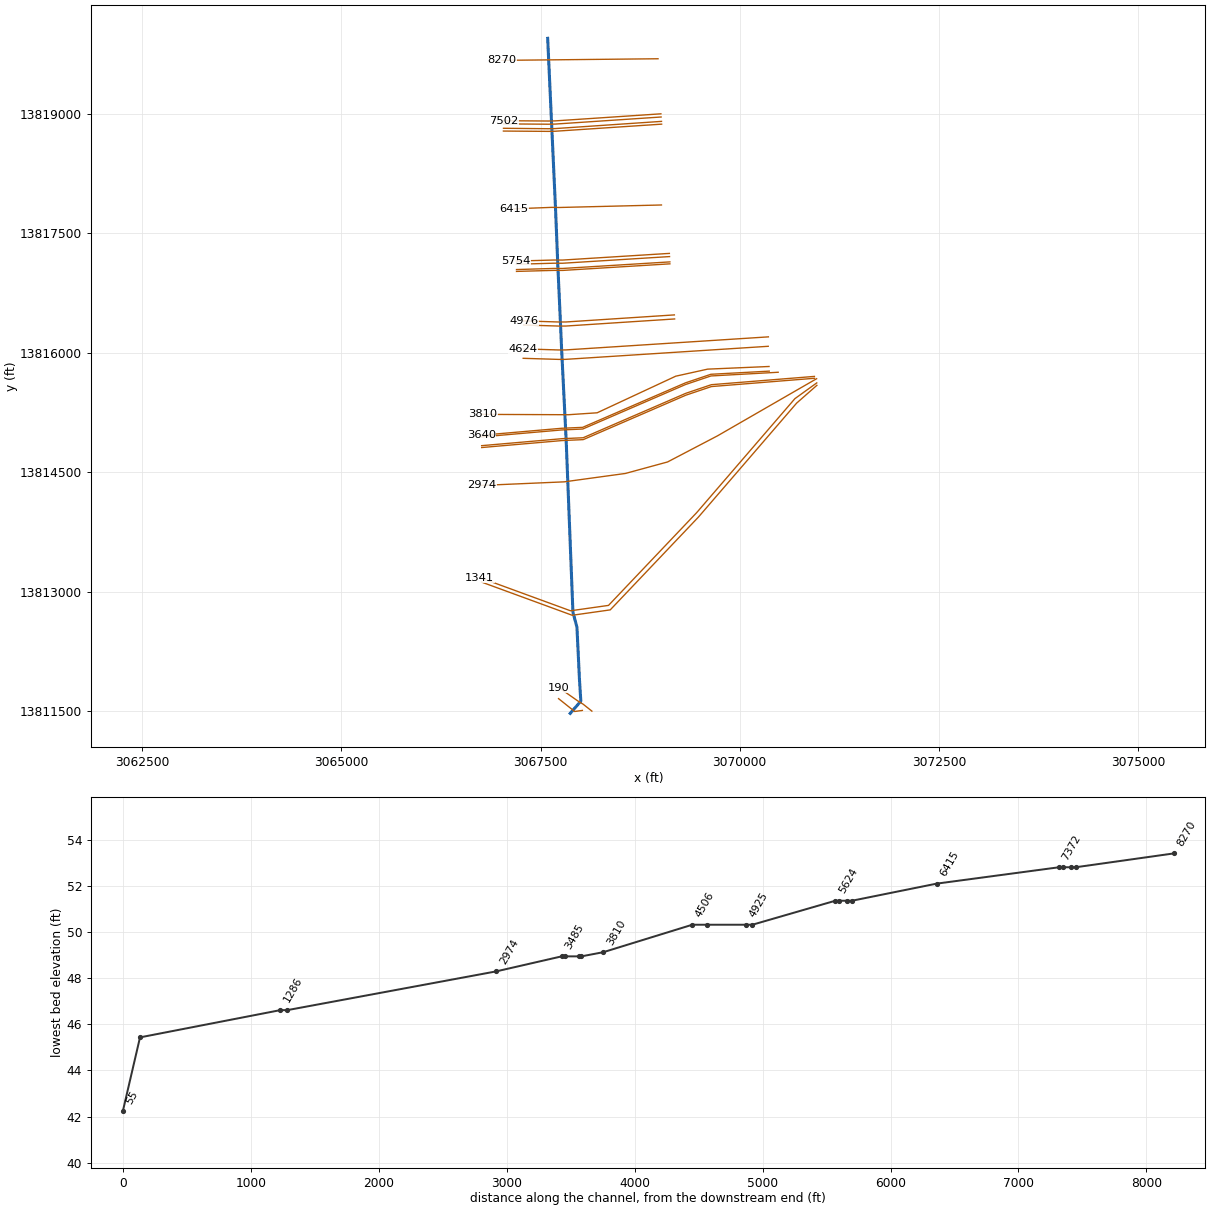
--- D144-00-00.prj (project) ---

Proj Title=D144-00-00
Current Plan=p05
Default Exp/Contr=.3,.1
English Units
Geom File=g03
Flow File=f03
Flow File=f04
Plan File=p04
Plan File=p05
Y Axis Title=Elevation (NGVD - 1995 Releveling)
X Axis Title(PF)=Above Brays Bayou (D100-00-00)
X Axis Title(XS)=Station
BEGIN DESCRIPTION:
Brays Bayou Watershed
Tributary 19.77
HCFCD Unit D144-00-00
Flood Hazard & Floodway Model
10, 2, 1, 0.2% Event
Filename D144.prj
Prepared by: Dodson & Associates, Inc.   Date: September 2003
Reviewed by:____________________	 Date:_________
STATUS (Final RAS)
FOR FLOOD HARZARD RECOVERY DATA ONLY,03/02/2004
Will Be Voided Upon Release of The Preliminary DFIRM
END DESCRIPTION:
DSS Export Rating Curves= 0
DSS Export Rating Curve Sorted= 0
DSS Export Volume Flow Curves= 0
DXF OffsetX= 0
DXF OffsetY= 0
DXF ScaleX= 1
DXF ScaleY= 10

--- D144-00-00.p05 (plan) ---

Plan Title=Floodway
Version=Version 3.0.1  Mar 2001
Short Identifier=Floodway0607
Geom File=g03
Flow File=f04
Subcritical Flow
K Sum by GR= 0
Std Step Tol= 0.01
Critical Tol= 0.01
Num of Std Step Trials= 20
Max Error Tol= 0.3
Flow Tol Ratio= 0.001
Split Flow NTrial= 30
Split Flow Tol= 0.02
Split Flow Ratio= 0.02
Log Output Level= 0
Friction Slope Method= 1
Unsteady Friction Slope Method= 2
Parabolic Critical Depth
Global Vel Dist= 0 , 0 , 0
Global Log Level= 0
CheckData=True
Encroach Param=-1 ,0,0, 2
Encroach River=Tributary 19.77
Encroach Reach=Reach 0
Encroach Node=8270
       1 1342.64 1394.57
Encroach Node=7502
       1 1326.17 1408.57
Encroach Node=7462
       1 1354.56 1409.57
Encroach Node=7456
       1 1354.56 1410.57
Encroach Node=7406
       1 1358.64 1410.57
Encroach Node=7372
       1 1354.56 1409.57
Encroach Node=6415
       1  1301.5 1367.83
Encroach Node=5754
       1 1371.71 1446.71
Encroach Node=5714
       1 1374.18 1449.18
Encroach Node=5709
       1 1374.18 1449.18
Encroach Node=5649
       1 1375.34 1441.72
Encroach Node=5624
       1 1373.34 1439.72
Encroach Node=4976
       1 1399.72 1466.09
Encroach Node=4925
       1 1399.72 1466.09
Encroach Node=4919
       1 1399.72 2637.09
Encroach Node=4624
       1 2570.72 2637.09
Encroach Node=4506
       1 2562.72 2637.16
Encroach Node=3810
       1 2628.98 2724.08
Encroach Node=3640
       1 2663.65  2729.1
Encroach Node=3619
       1 2773.65  2839.1
Encroach Node=3614
       1 2773.65  3294.1
Encroach Node=3509
       1 3228.65  3294.1
Encroach Node=3485
       1 3228.65  3294.1
Encroach Node=2974
       1 3380.77 3468.17
Encroach Node=1341
       1 4236.22 4318.85
Encroach Node=1286
       1 4251.22 4333.85
Encroach Node=739
       1  162.99 4333.85
Encroach Node=190
       1  162.99  217.38
Encroach Node=55
       1   92.99  147.38
Encroach Reach=D144-00-00_0001
Encroach Node=8270
       1 1342.64 1394.57
Encroach Node=7502
       1 1326.17 1408.57
Encroach Node=7462
       1 1354.56 1409.57
Encroach Node=7456
       1 1354.56 1410.57
Encroach Node=7406
       1 1358.64 1410.57
Encroach Node=7372
       1 1354.56 1409.57
Encroach Node=6415
       1  1301.5 1367.83
Encroach Node=5754
       1 1371.71 1446.71
Encroach Node=5714
       1 1374.18 1449.18
Encroach Node=5709
       1 1374.18 1449.18
Encroach Node=5649
       1 1375.34 1441.72
Encroach Node=5624
       1 1373.34 1439.72
Encroach Node=4976
       1 1399.72 1466.09
Encroach Node=4925
       1 1399.72 1466.09
Encroach Node=4919
       1 1399.72 2637.09
Encroach Node=4624
       1 2570.72 2637.09
Encroach Node=4506
       1 2562.72 2637.16
Encroach Node=3810
       1 2628.98 2724.08
Encroach Node=3640
       1 2663.65  2729.1
Encroach Node=3619
       1 2773.65  2839.1
Encroach Node=3614
       1 2773.65  3294.1
Encroach Node=3509
       1 3228.65  3294.1
Encroach Node=3485
       1 3228.65  3294.1
Encroach Node=2974
       1 3380.77 3468.17
Encroach Node=1341
       1 4236.22 4318.85
Encroach Node=1286
       1 4251.22 4333.85
Encroach Node=739
       1  162.99 4333.85
Encroach Node=190
       1  162.99  217.38
Encroach Node=55
       1   92.99  147.38
Computation Interval=1HOUR
Output Interval=1HOUR
Run HTab= 0
Run UNet= 0
Run PostProcess= 0
UNET Theta= 1
UNET ZTol= 0.02
UNET ZSATol= 0.1
UNET MxIter= 20
UNET MaxInSteps= 20
UNET DtIC= 0
UNET DtMin= 0
UNET MaxCRTS= 20
UNET WFStab= 2
UNET SFStab= 1
UNET WFX= 1
UNET SFX= 1
UNET Convert EG Bridges=-1
UNET Use Existing IB Tables=-1
Instantaneous Interval=1HOUR
Write IC File= 0
Write Velocity= 0
Write Detailed= 0

--- D144-00-00.p04 (plan) ---

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Plan Title=FEMA Effective June 2007
Short Identifier=FEMAeff0607
Geom File=g03
Flow File=f03
Encroach Param=-1 ,0,0, 0

--- D144-00-00.f04 (steady flow) ---

Flow Title=Floodway
Version=Version 3.0.1  Mar 2001
Number of Profiles= 2
Profile Names=1PCT_100yr,1PCTFloodway_100yrFW
River Rch & RM=Tributary 19.77,D144-00-00_0001 ,8270
     452     452
River Rch & RM=Tributary 19.77,D144-00-00_0001 ,6415
     489     489
River Rch & RM=Tributary 19.77,D144-00-00_0001 ,5624
     547     547
River Rch & RM=Tributary 19.77,D144-00-00_0001 ,4506
     637     637
River Rch & RM=Tributary 19.77,D144-00-00_0001 ,2974
     749     749
River Rch & RM=Tributary 19.77,D144-00-00_0001 ,1341
     856     856
Boundary for River Rch & Prof#=Tributary 19.77,D144-00-00_0001 , 1
Up Type= 0
Dn Type= 1
Dn Known WS=48.09
Boundary for River Rch & Prof#=Tributary 19.77,D144-00-00_0001 , 2
Up Type= 0
Dn Type= 1
Dn Known WS=48.09
DSS Import GetInterval= 0
DSS Import GetPeak= 0
DSS Import FillOption= 0

--- D144-00-00.f03 (steady flow) ---

Flow Title=FEMA Effective June 2007
Version=Version 3.0.1  Mar 2001
Number of Profiles= 4
Profile Names=10PCT_10yr,2PCT_50yr,1PCT_100yr,0.2PCT_500yr
River Rch & RM=Tributary 19.77,D144-00-00_0001 ,8270
     289     397     452     595
River Rch & RM=Tributary 19.77,D144-00-00_0001 ,6415
     309     428     489     648
River Rch & RM=Tributary 19.77,D144-00-00_0001 ,5624
     340     477     547     732
River Rch & RM=Tributary 19.77,D144-00-00_0001 ,4506
     389     553     637     866
River Rch & RM=Tributary 19.77,D144-00-00_0001 ,2974
     447     647     749    1035
River Rch & RM=Tributary 19.77,D144-00-00_0001 ,1341
     502     737     856    1198
Boundary for River Rch & Prof#=Tributary 19.77,D144-00-00_0001 , 1
Up Type= 0
Dn Type= 3
Dn Slope=.001
Boundary for River Rch & Prof#=Tributary 19.77,D144-00-00_0001 , 2
Up Type= 0
Dn Type= 3
Dn Slope=.001
Boundary for River Rch & Prof#=Tributary 19.77,D144-00-00_0001 , 3
Up Type= 0
Dn Type= 3
Dn Slope=.001
Boundary for River Rch & Prof#=Tributary 19.77,D144-00-00_0001 , 4
Up Type= 0
Dn Type= 3
Dn Slope=.001
DSS Import GetInterval= 0
DSS Import GetPeak= 0
DSS Import FillOption= 0

--- D144-00-00.g03 (geometry) ---

Geom Title=D144-00-00 June 2007
Version=Version 3.0.1  Mar 2001

River Reach=Tributary 19.77 ,D144-00-00_0001
Reach XY= 30
      3067588.83    13819944.787      3067588.84    13819944.707
     3067688.528    13817781.092     3067716.884    13817078.488
     3067748.391    13816391.638     3067764.145     13816032.46
     3067820.857    13814901.362     3067905.926     13812739.99
     3067956.336    13812551.952     3067988.241      13811887.5
     3067988.391     13811885.24     3067989.211      13811872.5
     3067989.291     13811871.14     3067990.181      13811857.5
     3067990.201     13811857.05     3067993.841     13811800.69
     3067994.051      13811797.5     3067995.011      13811782.5
     3067995.661     13811772.51     3067995.981      13811767.5
     3067997.481     13811744.33     3067997.921      13811737.5
      3067998.44    13811729.307     3068000.821      13811692.5
     3068001.111     13811687.96     3068001.791      13811677.5
     3068002.583    13811665.106     3068002.931     13811659.78
     3068005.254    13811623.775      3067871.78    13811469.906

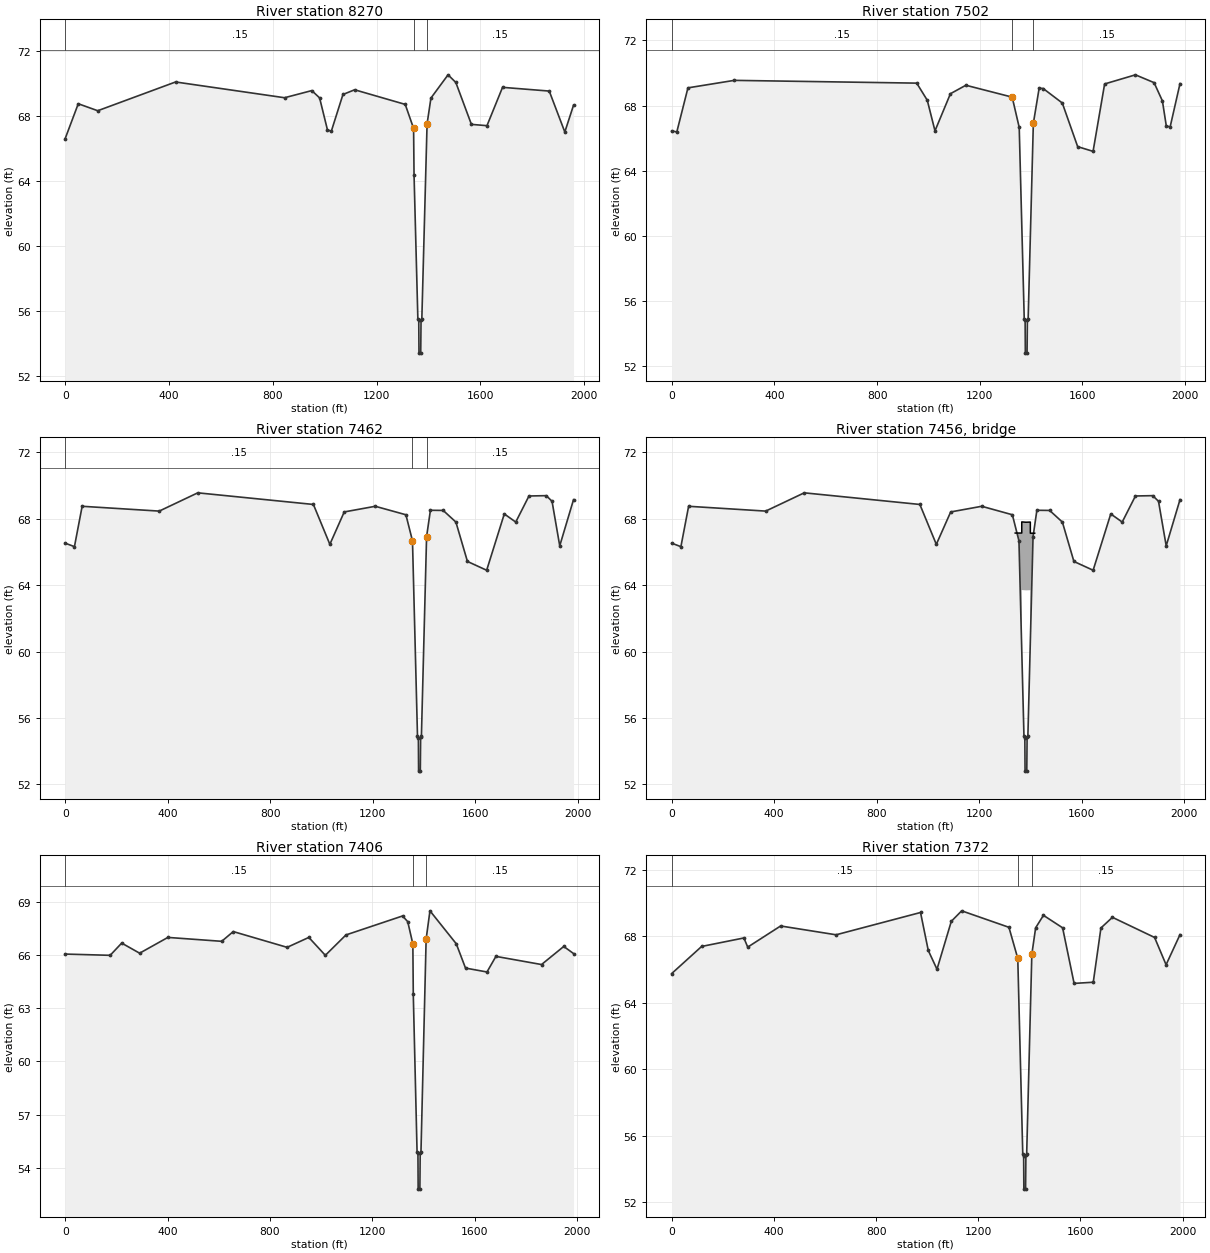
Type RM Length L Ch R = 1 ,8270    ,763.91,767.5,767.45
BEGIN DESCRIPTION:
Added Cross Section to Meet LODS
END DESCRIPTION:
XS GIS Cut Line= 2
      3068974.56    13819688.395      3067015.66    13819668.312
#Sta/Elev= 30
       0   66.61   50.33   68.75  125.34   68.32  425.35   70.09  845.37   69.12
  950.38   69.56  980.38   69.11 1010.38   67.16 1025.38   67.05 1070.39   69.32
 1115.39   69.61  1310.4   68.71 1342.64   67.23 1344.34   64.38 1359.11    55.5
 1362.55   55.42 1363.37   53.42  1370.1    53.4 1371.34   55.43 1374.36   55.49
 1394.57   67.51 1409.49    69.1 1475.41   70.53 1505.41   70.06 1565.41   67.48
 1625.42    67.4 1685.42   69.76 1865.43   69.53 1925.43   67.01 1959.01   68.66
#Mann= 3 , 0 , 0
       0     .15       0 1342.64    .015       0 1394.57     .15       0
#XS Ineff= 2 , 0
       0    1225            1417       0
Permanent Ineff=
       F       F
Bank Sta=1342.64,1394.57
XS Rating Curve= 0
Exp/Cntr=.3,.1

Type RM Length L Ch R = 1 ,7502    ,39.92,40,40.06
BEGIN DESCRIPTION:
7502.356--u/s appraoch Neff St Bridge; copied survey from 7406
END DESCRIPTION:
XS GIS Cut Line= 4
      3069010.72      13818997.1     3067682.552     13818908.37
     3067595.675      13818906.7     3067033.959     13818910.64
#Sta/Elev= 30
       0   66.45      20   66.38   63.36   69.09  243.76   69.55  954.36   69.38
  995.43   68.33  1025.5   66.45 1085.63   68.73 1145.77   69.25 1326.17   68.52
 1353.56   66.66 1373.11    54.9 1376.55   54.82 1377.37   52.82  1384.1    52.8
 1385.34   54.83 1388.36   54.89 1408.57   66.91  1431.2   69.07  1446.8   69.05
 1521.28   68.16  1581.2   65.48  1641.2   65.19  1686.2   69.33 1806.21   69.89
 1878.78   69.41 1911.21   68.29 1926.21   66.77 1941.21   66.68 1979.75   69.35
#Mann= 3 , 0 , 0
       0     .15       0 1326.17    .015       0 1408.57     .15       0
#XS Ineff= 2 , 0
       0    1218            1425       0
Permanent Ineff=
       T       T
Bank Sta=1326.17,1408.57
XS Rating Curve= 0
Exp/Cntr=.5,.3

Type RM Length L Ch R = 1 ,7462    ,56.44,56.63,56.63
BEGIN DESCRIPTION:
7462.353--u/s face Neff St Bridge; copied survey from 7406
END DESCRIPTION:
XS GIS Cut Line= 4
      3069013.43     13818957.19     3067682.411     13818868.37
     3067595.534      13818866.7     3067033.679     13818870.64
#Sta/Elev= 30
       0   66.52   36.01   66.31   66.08   68.74  366.74   68.45  517.08   69.55
  968.08   68.85 1032.26   66.45 1088.35    68.4 1209.45   68.74 1328.88   68.23
 1354.56   66.66 1374.11    54.9 1377.55   54.82 1378.37   52.82  1385.1    52.8
 1386.34   54.83 1389.36   54.89 1409.57   66.91 1424.49    68.5 1474.33   68.49
 1523.91   67.79 1568.91   65.42 1643.91   64.89 1712.67   68.28 1757.35   67.79
 1808.92   69.36 1876.52   69.38 1898.92   69.04 1928.92   66.36 1982.74   69.14
#Mann= 3 , 0 , 0
       0     .15       0 1354.56    .015       0 1409.57     .15       0
#XS Ineff= 2 , 0
       0    1220            1427       0
Permanent Ineff=
       T       T
Bank Sta=1354.56,1409.57
XS Rating Curve= 0
Exp/Cntr=.5,.3

Type RM Length L Ch R = 3 ,7456    ,,,
BEGIN DESCRIPTION:
Neff Street Bridge
END DESCRIPTION:
Bridge Culvert--1,0,-1,-1, 0
Deck Dist Width WeirC Skew NumUp NumDn MinLoCord MaxHiCord MaxSubmerge Is_Ogee
8.3,40,2.6,0, 7, 7, , , .95, 0, 0,0,,
    1340  1365.5  1365.5    1382    1399    1399    1416
   67.13   67.13    67.8   67.78   67.79   67.12   67.12
                    63.7   63.68   63.69
    1341  1366.5  1366.5    1383    1400    1400    1417
   67.13   67.13    67.8   67.78   67.79   67.12   67.12
                    63.7   63.68   63.69
BR Coef=-1 , 0 , 0 ,, 0 ,,,.8,-1,,0,
WSPro=,,,, 1 ,,,, 0 ,,,, 0 ,,,,-1 ,-1 ,-1 , 0 , 0 , 0 , 0 , 0
BC Design=,, 0 ,, 0 ,,,,,,

Type RM Length L Ch R = 1 ,7406    ,33.37,33.37,33.49
BEGIN DESCRIPTION:
7405.721--d/s face Neff St Bridge; surveyed channel
END DESCRIPTION:
XS GIS Cut Line= 4
     3069017.784    13818902.249      3067682.25    13818811.742
     3067595.372    13818810.072     3067034.292    13818815.589
#Sta/Elev= 30
       0   66.06  175.69   65.99  220.79   66.68  290.87   66.11   401.2      67
  611.68   66.78  656.79   67.33  867.27   66.44  952.09      67  1016.6   65.99
 1097.23   67.14  1318.3   68.21  1338.6   67.89 1358.64   66.63 1360.34   63.78
 1375.11    54.9 1378.55   54.82 1379.37   52.82  1386.1    52.8 1387.34   54.83
 1390.36   54.89 1410.57   66.91 1425.49    68.5 1528.37   66.64 1564.43   65.27
 1648.37   65.05 1683.27   65.93 1861.53   65.47 1948.39   66.49  1986.6   66.09
#Mann= 3 , 0 , 0
       0     .15       0 1358.64    .015       0 1410.57     .15       0
#XS Ineff= 2 , 0
       0    1223            1428       0
Permanent Ineff=
       T       T
Bank Sta=1358.64,1410.57
XS Rating Curve= 0
Exp/Cntr=.5,.3

Type RM Length L Ch R = 1 ,7372    ,961.04,956.99,956.15
BEGIN DESCRIPTION:
7372.347--d/s exit Neff St Bridge;  copied survey from 7406
END DESCRIPTION:
XS GIS Cut Line= 4
      3069019.52      13818867.4     3067682.095     13818778.37
     3067595.218      13818776.7     3067033.047     13818780.65
#Sta/Elev= 30
       0   65.75  117.28   67.38  282.64   67.89  297.68   67.34  426.38   68.61
  643.44   68.08  973.96   69.42 1004.24   67.14 1038.38   66.01 1094.44   68.89
 1135.02   69.52 1319.93   68.53 1354.56   66.66 1374.11    54.9 1377.55   54.82
 1378.37   52.82  1385.1    52.8 1386.34   54.83 1389.36   54.89 1409.57   66.91
 1424.49    68.5    1455   69.25    1530    68.5    1575   65.16    1650   65.23
    1680   68.49    1725   69.13 1890.01   67.92 1935.01   66.28 1989.46   68.09
#Mann= 3 , 0 , 0
       0     .15       0 1354.56    .015       0 1409.57     .15       0
#XS Ineff= 2 , 0
       0    1223            1427       0
Permanent Ineff=
       T       T
Bank Sta=1354.56,1409.57
XS Rating Curve= 0
Exp/Cntr=.3,.1

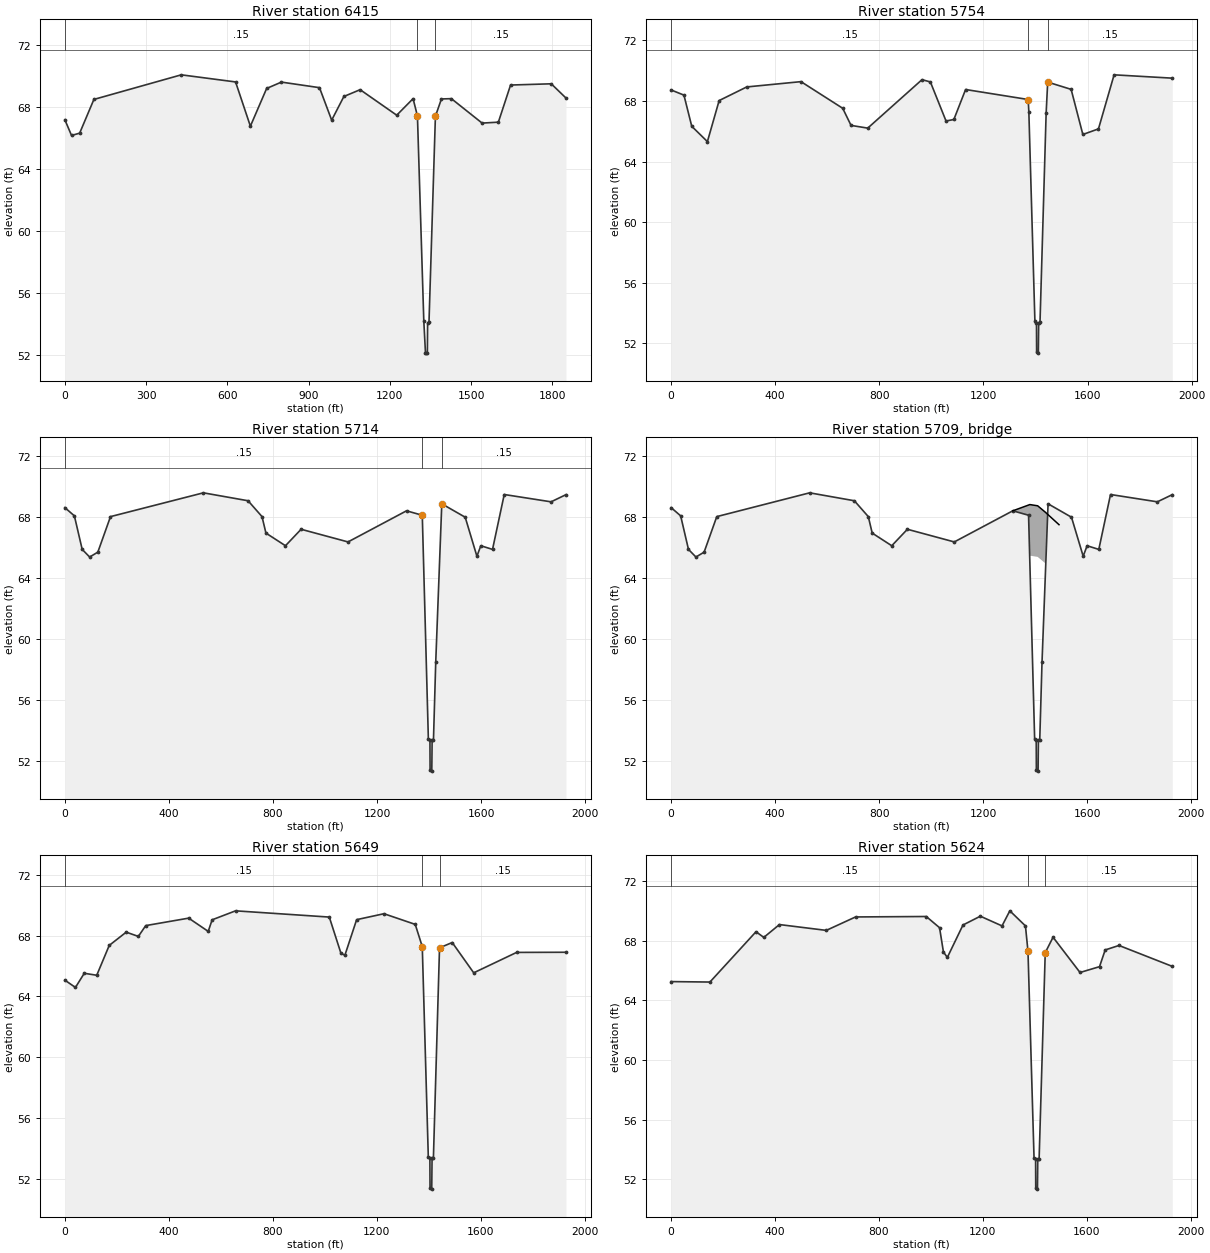
Type RM Length L Ch R = 1 ,6415    ,659.39,661.08,661.45
BEGIN DESCRIPTION:
6415.353--surveyed channel
END DESCRIPTION:
XS GIS Cut Line= 4
     3069017.158    13817852.604     3067732.149    13817821.105
     3067640.216    13817822.746     3067168.118    13817804.452
#Sta/Elev= 30
       0   67.18   24.67   66.16   54.67   66.31  107.21   68.49  429.79   70.08
  630.19   69.62  684.86   66.76  744.88    69.2  799.38   69.61  939.94   69.25
  984.95   67.15 1029.97   68.68 1089.99   69.12 1225.03   67.47  1285.4   68.54
  1301.5   67.42 1324.99   54.17 1331.12   52.12 1334.53   52.09 1338.14   52.12
 1339.09   54.05 1344.18   54.11 1367.83    67.4 1390.07   68.52 1426.76   68.54
 1540.18   66.96 1600.23   67.02 1645.26   69.42 1795.37    69.5 1849.79   68.58
#Mann= 3 , 0 , 0
       0     .15       0  1301.5    .015       0 1367.83     .15       0
#XS Ineff= 2 , 0
       0    1180            1392       0
Permanent Ineff=
       T       T
Bank Sta=1301.5,1367.83
XS Rating Curve= 0
Exp/Cntr=.3,.1

Type RM Length L Ch R = 1 ,5754    ,39.96,40.05,40.01
BEGIN DESCRIPTION:
5754.272--u/s approach Triola Lane Bridge; copied survey from 5649
END DESCRIPTION:
XS GIS Cut Line= 4
       3069116.6     13817244.75     3067775.986    13817161.115
     3067667.261     13817161.59     3067194.131     13817148.61
#Sta/Elev= 30
       0   68.73    49.2   68.39   79.25   66.33  139.37   65.32  184.46   68.03
   290.5   68.93  498.88   69.28  659.17   67.52  691.23   66.39  755.35   66.21
  963.73   69.41  996.03   69.26 1056.15   66.68 1086.21   66.78  1131.3   68.76
 1371.71    68.1 1374.34   67.27 1397.57   53.46 1403.64   53.37 1404.17   51.42
 1410.73   51.35 1412.01   53.37 1417.19   53.39 1440.72   67.19 1446.71   69.25
 1536.74   68.77 1581.76   65.79 1641.78   66.16  1701.8   69.73 1925.25   69.51
#Mann= 3 , 0 , 0
       0     .15       0 1371.71    .015       0 1446.71     .15       0
#XS Ineff= 2 , 0
       0    1235            1461       0
Permanent Ineff=
       T       T
Bank Sta=1371.71,1446.71
XS Rating Curve= 0
Exp/Cntr=.5,.3

Type RM Length L Ch R = 1 ,5714    ,65.43,65.52,65.51
BEGIN DESCRIPTION:
5714.226--u/s face Triola Lane Bridge; copied survey from 5649
END DESCRIPTION:
XS GIS Cut Line= 4
      3069119.07     13817204.83     3067776.534    13817121.115
     3067667.809     13817121.59     3067195.228     13817108.62
#Sta/Elev= 30
       0   68.63   36.64   68.09    66.7   65.89   95.36   65.39  126.82   65.71
   175.5   68.04   532.6    69.6  704.45   69.08  758.04   68.04  773.07   66.96
  848.21   66.13  908.33   67.21 1088.68   66.38 1313.53   68.42 1374.18   68.13
 1397.57   53.46 1403.64   53.37 1404.17   51.42 1410.73   51.35 1412.01   53.37
 1417.19   53.39 1425.91    58.5 1449.18   68.88 1539.21      68 1584.23   65.44
 1599.23   66.13 1644.25   65.89 1689.27   69.49 1869.34   69.01 1926.63   69.48
#Mann= 3 , 0 , 0
       0     .15       0 1374.18    .015       0 1449.18     .15       0
#XS Ineff= 2 , 0
       0    1236            1462       0
Permanent Ineff=
       T       T
Bank Sta=1374.18,1449.18
XS Rating Curve= 0
Exp/Cntr=.5,.3

Type RM Length L Ch R = 3 ,5709    ,,,
BEGIN DESCRIPTION:
Triola Lane Bridge
END DESCRIPTION:
Bridge Culvert--1,0,-1,-1, 0
Deck Dist Width WeirC Skew NumUp NumDn MinLoCord MaxHiCord MaxSubmerge Is_Ogee
7.7,40,2.6,0, 5, 5, , , .95, 0, 0,0,,
 1313.53  1379.1  1409.2  1439.3 1491.26
   68.42   68.83   68.75   68.32   67.51
           65.48    65.4   64.97
 1312.86 1378.43 1408.53 1438.63 1490.59
   68.42   68.83   68.75   68.32   67.51
           65.48    65.4   64.97
BR Coef=-1 , 0 , 0 ,, 0 ,,,.8,-1,,0,
WSPro=,,,, 1 ,,,, 0 ,,,, 0 ,,,,-1 ,-1 ,-1 , 0 , 0 , 0 , 0 , 0
BC Design=,, 0 ,, 0 ,,,,,,

Type RM Length L Ch R = 1 ,5649    ,24.53,24.58,24.5
BEGIN DESCRIPTION:
5648.704--d/s face Triola Lane Bridge; surveyed channel
END DESCRIPTION:
XS GIS Cut Line= 4
     3069123.176    13817138.158     3067777.423    13817055.669
     3067668.699    13817056.143     3067197.614    13817041.878
#Sta/Elev= 30
       0   65.07   40.75   64.59   74.73   65.52  122.76   65.39  170.79   67.35
  236.12   68.22  282.85   67.94  311.26   68.65  476.57   69.14  551.71   68.27
  566.74   69.03  656.91   69.62 1017.58   69.21 1062.67   66.82 1077.69   66.71
 1122.78   69.04 1227.98   69.43 1348.28   68.73 1375.34   67.27 1398.57   53.46
 1404.64   53.37 1405.17   51.42 1411.73   51.35 1413.01   53.37 1418.19   53.39
 1441.72   67.19 1490.59   67.54 1573.26   65.55 1738.33   66.89 1928.31    66.9
#Mann= 3 , 0 , 0
       0     .15       0 1375.34    .015       0 1441.72     .15       0
#XS Ineff= 2 , 0
       0    1238            1467       0
Permanent Ineff=
       T       T
Bank Sta=1375.34,1441.72
XS Rating Curve= 0
Exp/Cntr=.5,.3

Type RM Length L Ch R = 1 ,5624    ,648.48,648.41,646.62
BEGIN DESCRIPTION:
5624.123--d/s exit Triola Lane Bridge; copied survey from 5649
END DESCRIPTION:
XS GIS Cut Line= 4
     3069123.521    13817113.605     3067777.768    13817031.115
     3067669.043     13817031.59     3067197.695     13817018.66
#Sta/Elev= 30
       0   65.25  149.33   65.22  326.63   68.59  356.69   68.21   416.8   69.07
  597.14   68.68  709.66   69.58  981.82   69.61 1032.96   68.86 1047.98   67.23
 1063.01   66.87 1123.12   69.04 1189.95   69.63 1273.41   68.98 1303.46   69.99
 1363.55   68.98 1373.34   67.27 1396.57   53.46 1402.64   53.37 1403.17   51.42
 1409.73   51.35 1411.01   53.37 1416.19   53.39 1439.72   67.19 1469.81   68.22
 1573.59   65.86 1648.62   66.25 1670.39   67.37 1723.65   67.67 1928.53   66.27
#Mann= 3 , 0 , 0
       0     .15       0 1373.34    .015       0 1439.72     .15       0
#XS Ineff= 2 , 0
       0    1238            1469       0
Permanent Ineff=
       T       T
Bank Sta=1373.34,1439.72
XS Rating Curve= 0
Exp/Cntr=.3,.1

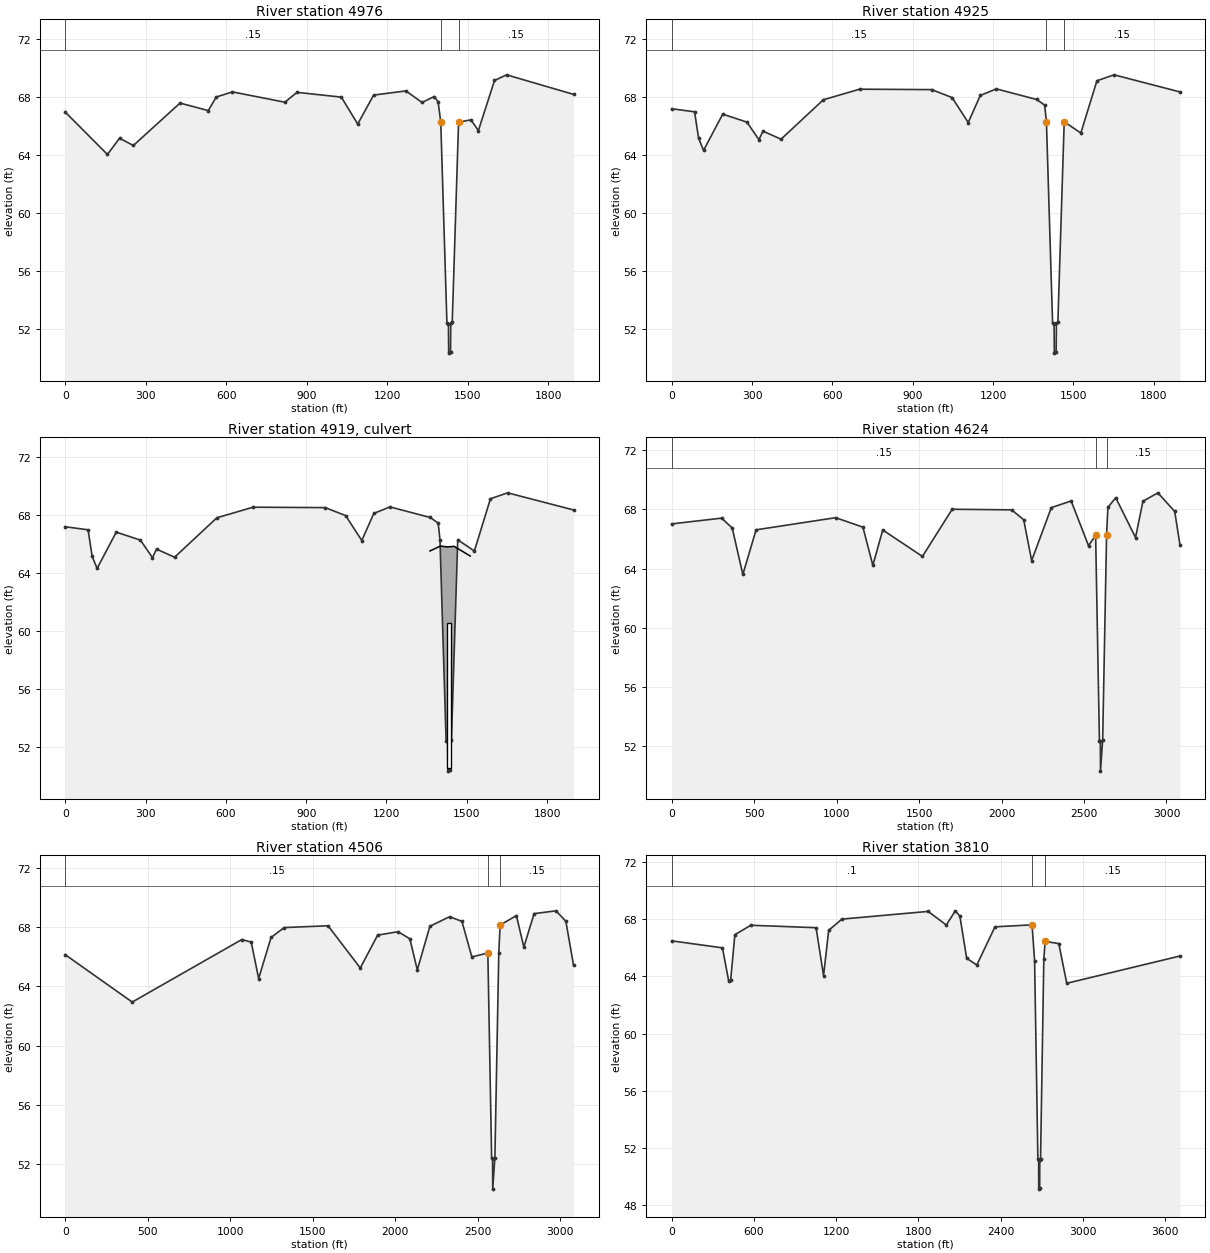
Type RM Length L Ch R = 1 ,4976    ,50.85,51.04,51.15
BEGIN DESCRIPTION:
4975.710--u/s approach S. Gessner culvert; copied survey from 4506
END DESCRIPTION:
XS GIS Cut Line= 4
      3069179.52     13816472.59     3067818.834    13816383.823
     3067732.976     13816383.44     3067288.067    13816396.989
#Sta/Elev= 30
       0   66.96  157.35   64.03  202.45   65.15     254   64.65  427.93   67.58
  533.15   67.06  563.21      68  623.34   68.35  818.76   67.64  863.85   68.32
  1029.2   67.99 1090.21   66.13 1149.46   68.13 1269.71   68.42 1329.84   67.62
 1374.91   68.03 1389.91   67.67 1399.72   66.25 1422.69   52.38 1428.27   52.32
 1429.22   50.31 1436.01   50.38 1436.99   52.39 1442.44   52.44 1466.09   66.26
  1512.1   66.42 1539.96   65.68 1599.98   69.14    1645   69.53 1894.55   68.18
#Mann= 3 , 0 , 0
       0     .15       0 1399.72    .015       0 1466.09     .15       0
#XS Ineff= 2 , 0
       0    1399            1466       0
Permanent Ineff=
       T       T
Bank Sta=1399.72,1466.09
XS Rating Curve= 0
Exp/Cntr=.5,.3

Type RM Length L Ch R = 1 ,4925    ,299.16,300.22,300.86
BEGIN DESCRIPTION:
4924.672--u/s face S. Gessner culvert; copied survey from 4506
END DESCRIPTION:
XS GIS Cut Line= 4
       3069182.8      13816421.7     3067818.097    13816332.823
     3067732.239     13816332.44      3067287.33    13816345.989
#Sta/Elev= 30
       0   67.16   85.48   66.95  100.51   65.13  119.09   64.29   190.7   66.79
  280.89   66.24  325.99   65.03  341.02   65.62  408.51   65.06   566.5   67.78
  701.78   68.51  971.27   68.48 1047.51   67.93 1107.64   66.21 1152.74   68.08
 1212.86   68.53 1363.18    67.8 1393.19   67.41 1399.72   66.25 1422.69   52.38
 1428.27   52.32 1429.22   50.31 1436.01   50.38 1436.99   52.39 1442.44   52.44
 1466.09   66.26 1528.23   65.49 1588.25   69.09 1652.29    69.5 1898.57   68.32
#Mann= 3 , 0 , 0
       0     .15       0 1399.72    .015       0 1466.09     .15       0
#XS Ineff= 2 , 0
       0    1417            1450       0
Permanent Ineff=
       T       T
Bank Sta=1399.72,1466.09
XS Rating Curve= 0
Exp/Cntr=.5,.3

Type RM Length L Ch R = 2 ,4919    ,,,
BEGIN DESCRIPTION:
South Gessner Culvert
END DESCRIPTION:
Bridge Culvert--1,0,-1,-1, 0
Deck Dist Width WeirC Skew NumUp NumDn MinLoCord MaxHiCord MaxSubmerge Is_Ogee
5.1,290,2.6,0, 5, 5, , , .95, 0, 0,0,,
  1362.3  1401.5    1427  1452.5 1512.94
   65.49   65.83   65.77   65.81   65.14
                                        
  2534.3  2573.5    2599  2624.5 2684.94
   65.49   65.83   65.77   65.81   65.14
                                        
Culvert=2,10,15,290,.015,.4,1,8,1,50.5,1432,50.5,2604,Culvert #1  , 0 ,5.1
Culvert Bottom n=.015
BC Design=,, 0 ,, 0 ,,,,,,

Type RM Length L Ch R = 1 ,4624    ,118.07,118.5,118.75
BEGIN DESCRIPTION:
4624.448--d/s face S. Gessner culvert; copied survey from 4506
END DESCRIPTION:
XS GIS Cut Line= 4
     3070359.783    13816196.901     3067813.759    13816032.823
     3067727.901     13816032.44     3067282.992    13816045.989
#Sta/Elev= 30
       0   67.02     303   67.41  367.26   66.74  431.53    63.6  511.86   66.62
  994.34   67.44 1159.68    66.8 1219.81   64.22 1279.93   66.61 1520.43   64.82
 1700.78   68.01 2061.55   67.97 2134.58    67.3 2182.78   64.54 2302.05   68.12
  2422.3   68.57 2527.52   65.55 2570.72   66.25 2593.69   52.38 2599.27   52.32
 2600.22   50.31 2613.44   52.44 2637.09   66.26 2645.16   68.14 2692.59   68.79
 2812.65    66.1 2857.67   68.55  2948.3   69.12 3050.24   67.86 3082.28   65.59
#Mann= 3 , 0 , 0
       0     .15       0 2570.72    .015       0 2637.09     .15       0
#XS Ineff= 2 , 0
       0    2584            2623       0
Permanent Ineff=
       T       T
Bank Sta=2570.72,2637.09
XS Rating Curve= 0
Exp/Cntr=.5,.3

Type RM Length L Ch R = 1 ,4506    ,695.89,695.87,696.76
BEGIN DESCRIPTION:
4505.947--surveyed channel
END DESCRIPTION:
XS GIS Cut Line= 4
      3070358.06    13816078.488     3067812.036     13815914.41
     3067726.178    13815914.027     3067281.269    13815927.576
#Sta/Elev= 30
       0   66.14   406.4   62.94 1070.64   67.16  1127.9   66.99 1172.99   64.53
 1248.14    67.3 1327.71   67.97 1593.86   68.09 1789.26   65.24 1894.48   67.46
 2018.57   67.69 2089.89   67.21 2134.98   65.11 2211.37   68.06 2330.38    68.7
 2405.54   68.39 2465.66   65.99 2562.72   66.25 2585.69   52.38 2591.27   52.32
 2592.22   50.31 2605.44   52.44 2629.09   66.26 2637.16   68.14 2735.89   68.78
 2780.91   66.65 2843.14   68.91    2976    69.1 3036.03   68.39 3082.28   65.43
#Mann= 3 , 0 , 0
       0     .15       0 2562.72    .015       0 2637.16     .15       0
#XS Ineff= 2 , 0
       0    2542            2650       0
Permanent Ineff=
       T       T
Bank Sta=2562.72,2637.16
XS Rating Curve= 0
Exp/Cntr=.3,.1

Type RM Length L Ch R = 1 ,3810    ,170.01,170.34,171.88
BEGIN DESCRIPTION:
3810.080--surveyed channel
END DESCRIPTION:
XS GIS Cut Line= 6
     3070368.037    13815824.934     3069596.656    13815791.683
     3069196.642    13815703.142        3068210.     13815243.62
     3067849.987    13815219.414     3066773.271      13815223.5
#Sta/Elev= 30
       0   66.49   370.6      66  415.73   63.69  430.77   63.78  460.86   66.92
  577.38   67.58 1053.37   67.41 1107.95   64.06 1145.54   67.23    1242   68.01
 1870.89   68.55 2003.16    67.6 2069.35   68.59 2102.45   68.22 2152.09   65.27
 2225.96    64.8 2358.37   67.47 2628.98   67.61 2647.61   65.07 2671.46   51.26
    2677   51.13 2677.66   49.12 2684.55   49.18 2685.21   51.18 2690.91   51.22
 2714.73   65.19 2724.08   66.45 2823.99    66.3 2882.06   63.52 3708.23   65.43
#Mann= 3 , 0 , 0
       0      .1       0 2628.98    .015       0 2724.08     .15       0
#XS Ineff= 2 , 0
       0    2459            2739       0
Permanent Ineff=
       T       T
Bank Sta=2628.98,2724.08
XS Rating Curve= 0
Exp/Cntr=.3,.1

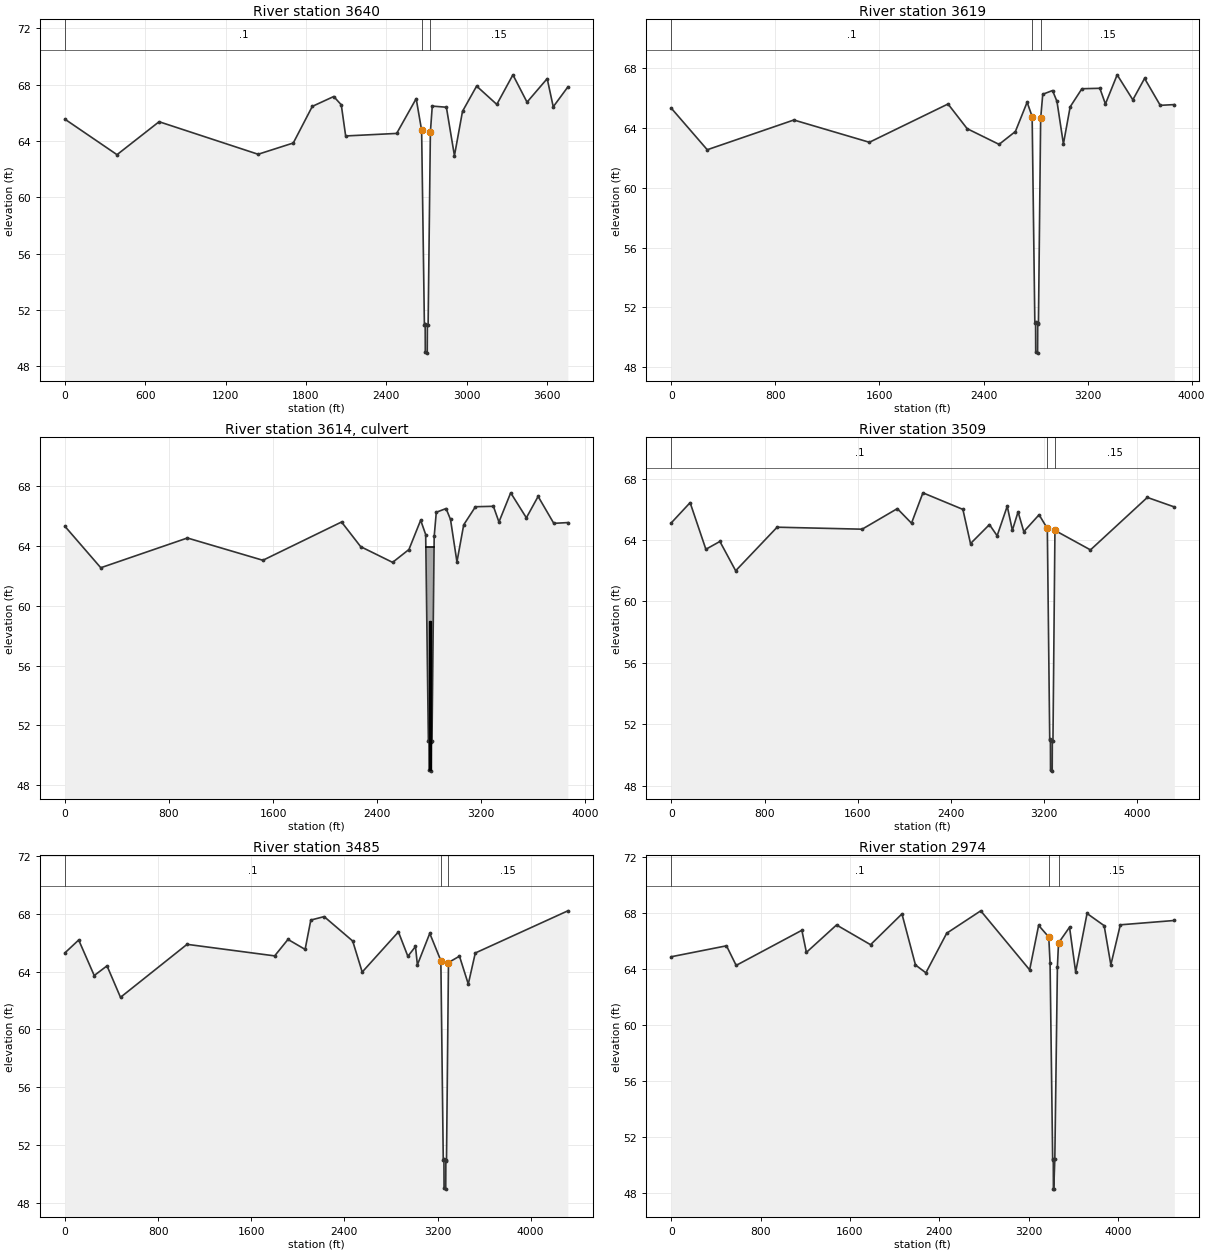
Type RM Length L Ch R = 1 ,3640    ,21.02,21.02,21.02
BEGIN DESCRIPTION:
3639.745--u/s approach Beechnut culverts; copied survey from 3485
END DESCRIPTION:
XS GIS Cut Line= 6
     3070370.802    13815766.743     3069637.661    13815727.022
     3069318.145    13815619.278     3068027.839    13815060.788
     3067764.403     13815049.25     3066753.716    13814961.462
#Sta/Elev= 30
       0   65.55  388.87   63.03  703.13   65.37 1442.59   63.06 1705.25   63.86
 1847.33   66.46 2007.35   67.16  2063.7   66.57 2096.39   64.36  2477.4   64.54
 2623.04   67.01 2663.65   64.76 2684.38   50.96 2690.12   51.04 2691.07      49
 2705.57   48.94 2706.62   50.92  2712.1   50.93  2729.1   64.63 2743.13   66.48
 2848.53    66.4 2908.75   62.96 2968.98   66.11 3074.38    67.9 3225.06    66.6
 3345.39    68.7 3450.79   66.76 3601.35   68.43 3646.52   66.43 3755.72   67.84
#Mann= 3 , 0 , 0
       0      .1       0 2663.65    .015       0  2729.1     .15       0
#XS Ineff= 2 , 0
       0    2640            2743       0
Permanent Ineff=
       T       T
Bank Sta=2663.65,2729.1
XS Rating Curve= 0
Exp/Cntr=.5,.3

Type RM Length L Ch R = 1 ,3619    ,109.68,109.67,109.7
BEGIN DESCRIPTION:
3618.724--u/s face Beechnut culverts; copied survey from 3485
END DESCRIPTION:
XS GIS Cut Line= 6
     3070482.684    13815752.569     3069638.593    13815706.022
     3069319.077    13815598.278     3068028.771    13815039.788
     3067765.335     13815028.25     3066754.648    13814940.462
#Sta/Elev= 30
       0   65.31   275.6   62.54  941.51   64.53 1522.08   63.04 2126.84    65.6
 2273.94   63.95 2519.36    62.9 2644.94   63.76 2735.13   65.72 2773.65   64.76
 2794.38   50.96 2800.12   51.04 2801.07      49 2815.57   48.94 2816.62   50.92
  2822.1   50.93  2839.1   64.63 2855.23   66.25 2930.51    66.5  2964.6   65.77
 3014.06   62.93 3066.02   65.41 3156.36   66.62 3294.37   66.65 3337.03    65.6
 3427.37   67.55 3547.83   65.88 3638.17   67.31 3758.62   65.51 3866.88   65.56
#Mann= 3 , 0 , 0
       0      .1       0 2773.65    .015       0  2839.1     .15       0
#XS Ineff= 2 , 0
       0    2750            2855       0
Permanent Ineff=
       T       T
Bank Sta=2773.65,2839.1
XS Rating Curve= 0
Exp/Cntr=.5,.3

Type RM Length L Ch R = 2 ,3614    ,,,
BEGIN DESCRIPTION:
Beechnut Culverts
END DESCRIPTION:
Bridge Culvert--1,0,-1,-1, 0
Deck Dist Width WeirC Skew NumUp NumDn MinLoCord MaxHiCord MaxSubmerge Is_Ogee
5,100,2.6,0, 5, 5, , , .95, 0, 0,0,,
    2774  2796.5    2807  2817.5  2838.7
   63.96   63.96   63.96   63.96   63.96
                                        
    3230  3252.5    3263  3273.5  3294.7
   63.96   63.96   63.96   63.96   63.96
                                        
Multiple Barrel Culv=2,10,10,100,.015,.4,1,8,1,49,49, 2,Culvert #1  , 0 ,5
 2801.75 3257.75 2812.25 3268.25
Culvert Bottom n=.015
BC Design=,, 0 ,, 0 ,,,,,,

Type RM Length L Ch R = 1 ,3509    ,23.53,23.57,23.52
BEGIN DESCRIPTION:
3509.059--d/s face Beechnut culverts; copied survey from 3485
END DESCRIPTION:
XS GIS Cut Line= 6
     3070937.665    13815700.511      3069643.89    13815596.465
     3069324.375    13815488.721     3068034.069    13814930.231
     3067770.633    13814918.693     3066759.945    13814830.905
#Sta/Elev= 30
       0   65.13  160.68   66.44  296.12    63.4  416.51   63.91  551.94      62
  907.85   64.84 1638.22   64.71 1940.32   66.05 2062.15    65.1 2160.22   67.08
 2503.46      66 2568.84   63.77  2731.5   65.01 2797.67   64.28 2884.37   66.21
 2928.43   64.64 2977.46   65.84  3026.5   64.55  3157.8   65.65 3228.65   64.76
 3249.38   50.96 3255.12   51.04 3256.07      49 3270.57   48.94 3271.62   50.92
  3277.1   50.93  3294.1   64.63  3599.2   63.36 4087.56   66.78 4319.45   66.16
#Mann= 3 , 0 , 0
       0      .1       0 3228.65    .015       0  3294.1     .15       0
#XS Ineff= 2 , 0
       0    3229            3294       0
Permanent Ineff=
       T       T
Bank Sta=3228.65,3294.1
XS Rating Curve= 0
Exp/Cntr=.5,.3

Type RM Length L Ch R = 1 ,3485    ,501.46,511.06,518.04
BEGIN DESCRIPTION:
3485.492--d/s exit Beechnut culverts; surveyed channel
END DESCRIPTION:
XS GIS Cut Line= 6
      3070938.22     13815676.97     3069644.445    13815572.924
      3069324.93     13815465.18     3068034.624     13814906.69
     3067771.188    13814895.152       3066760.5    13814807.364
#Sta/Elev= 30
       0    65.3  118.14   66.19  251.53   63.73  361.38    64.4  477.26   62.22
 1048.69   65.89 1801.24   65.09 1915.65   66.23 2062.76   65.54 2111.79   67.57
  2226.2   67.81 2471.38   66.12  2553.1   63.97 2864.25   66.75 2945.38   65.06
 3010.75   65.74  3027.1   64.47 3133.45   66.65 3228.65   64.76 3249.38   50.96
 3255.12   51.04 3256.07      49 3270.57   48.94 3271.62   50.92  3277.1   50.93
  3294.1   64.63 3388.54   65.07 3464.24   63.14 3524.47   65.29 4319.45   68.21
#Mann= 3 , 0 , 0
       0      .1       0 3228.65    .015       0  3294.1     .15       0
#XS Ineff= 2 , 0
       0    3218            3305       0
Permanent Ineff=
       T       T
Bank Sta=3228.65,3294.1
XS Rating Curve= 0
Exp/Cntr=.3,.1

Type RM Length L Ch R = 1 ,2974    ,1632.82,1633.68,1591.77
BEGIN DESCRIPTION:
2974.433--surveyed channel
END DESCRIPTION:
XS GIS Cut Line= 6
     3070965.139     13815671.45     3069720.179    13814953.848
     3069094.202    13814626.414     3068564.529    13814481.958
     3067795.971    13814376.624     3066759.376    13814331.735
#Sta/Elev= 30
       0    64.9  493.59   65.68  580.16   64.28 1168.82   66.79 1209.38   65.21
 1479.49   67.17  1784.2   65.76 2065.55   67.96 2186.63   64.31 2279.92   63.75
  2466.5   66.58 2771.39   68.18 3209.61   63.96 3289.93   67.14 3380.77   66.31
 3392.49   64.45 3415.73   50.42 3421.45   50.34 3422.39    48.3 3425.52   48.29
 3435.14   50.45 3458.22   64.17 3468.17   65.88 3566.88   67.01 3621.79   63.81
 3723.82   67.99 3877.03   67.12 3937.08   64.32    4022   67.18 4505.74   67.49
#Mann= 3 , 0 , 0
       0      .1       0 3380.77    .015       0 3468.17     .15       0
#XS Ineff= 2 , 0
       0    3201            3477       0
Permanent Ineff=
       T       T
Bank Sta=3380.77,3468.17
XS Rating Curve= 0
Exp/Cntr=.3,.1

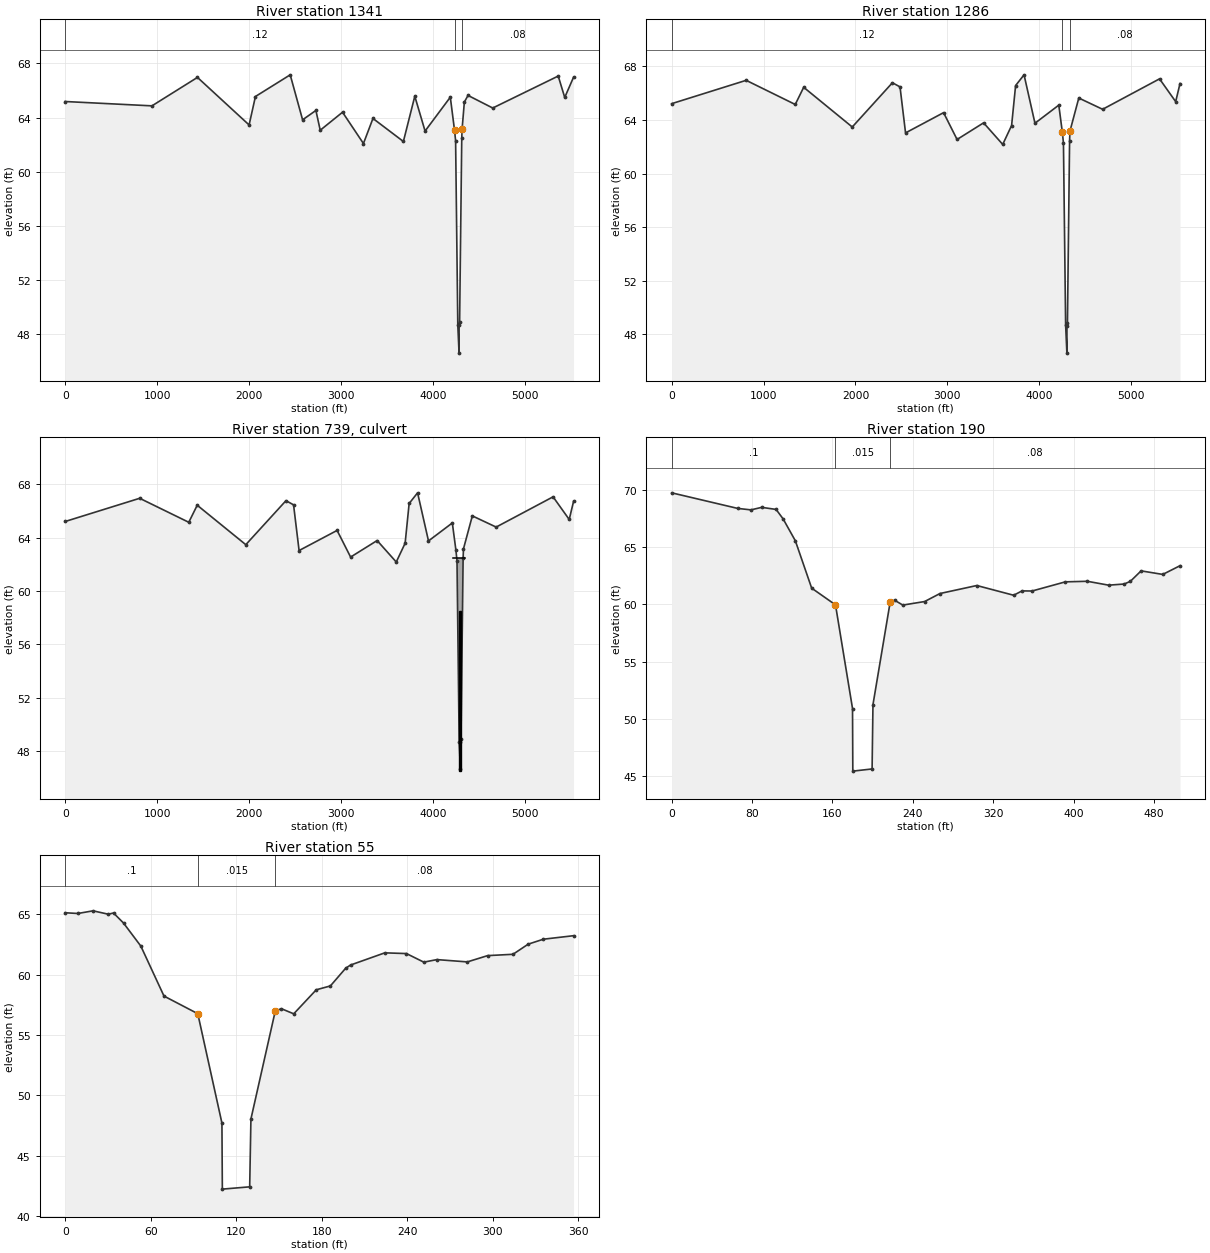
Type RM Length L Ch R = 1 ,1341    ,59.7,54.6,47.77
BEGIN DESCRIPTION:
1340.756--u/s approach golfcourse culvert; surveyed channel
END DESCRIPTION:
XS GIS Cut Line= 6
     3070967.409       13815619.     3070692.863    13815421.364
     3069460.157    13813990.807      3068352.66    13812825.526
     3067875.356    13812757.898     3066736.903    13813174.777
#Sta/Elev= 30
       0   65.18  943.95   64.86 1439.02   66.96 2000.97   63.45  2069.9   65.55
 2448.28   67.15 2583.04   63.83  2727.9   64.52 2774.88   63.06 3017.62   64.39
 3245.25   62.08 3348.72   63.93 3679.82   62.23 3803.98   65.57 3915.83      63
 4190.45    65.5 4236.22   63.07 4248.08   62.28 4271.82    48.7 4285.62   46.61
 4286.28   48.65 4291.59   48.88 4314.93   62.46 4318.85   63.16  4343.2   65.14
 4383.13   65.63 4652.06    64.7 5364.66   67.06 5435.46   65.48 5531.24   66.97
#Mann= 3 , 0 , 0
       0     .12       0 4236.22    .015       0 4318.85     .08       0
#XS Ineff= 2 , 0
       0    4236            4319       0
Permanent Ineff=
       T       T
Bank Sta=4236.22,4318.85
XS Rating Curve= 0
Exp/Cntr=.5,.3

Type RM Length L Ch R = 1 ,1286    ,1169.16,1096.44,954.37
BEGIN DESCRIPTION:
1286.155--u/s face golfcourse culvert; copied survey from 1341
END DESCRIPTION:
XS GIS Cut Line= 6
      3070968.74    13815588.229     3070714.379    13815365.088
     3069481.673    13813934.531     3068374.176     13812769.25
     3067896.872    13812701.622     3066758.418    13813118.501
#Sta/Elev= 30
       0   65.21   810.4   66.95 1344.65   65.15 1436.56   66.43 1965.07   63.47
 2402.02   66.77 2484.79   66.46 2544.91   63.03 2958.61   64.54 3105.61   62.54
 3394.08   63.78 3602.27   62.17 3698.92   63.58 3742.46   66.56 3834.38   67.36
 3953.05   63.75 4212.42    65.1 4251.22   63.07 4263.08   62.28 4286.82    48.7
 4300.62   46.61 4301.28   48.65 4306.59   48.88 4329.93   62.46 4333.85   63.16
 4430.09   65.63  4689.4   64.79 5308.66   67.06 5484.38   65.36 5531.32   66.71
#Mann= 3 , 0 , 0
       0     .12       0 4251.22    .015       0 4333.85     .08       0
#XS Ineff= 2 , 0
       0    4251            4334       0
Permanent Ineff=
       T       T
Bank Sta=4251.22,4333.85
XS Rating Curve= 0
Exp/Cntr=.5,.3

Type RM Length L Ch R = 2 ,739     ,,,
BEGIN DESCRIPTION:
Westwood Country Club Golfcourse Culvert
END DESCRIPTION:
Bridge Culvert--1,0,-1,-1, 0
Deck Dist Width WeirC Skew NumUp NumDn MinLoCord MaxHiCord MaxSubmerge Is_Ogee
3.2,1090,2.6,0, 2, 4, , , .95, 0, 0,0,,
    4225    4350
   62.48   62.48
                
     134     154     222     305
      62   62.48   62.48    61.6
                                
Multiple Barrel Culv=2,12,10,1090,.015,.4,1,8,1,46.48,45.01, 2,Culvert #1  , 0 ,3.2
    4291     184  4301.8   194.8
Culvert Bottom n=.015
BC Design=,, 0 ,, 0 ,,,,,,

Type RM Length L Ch R = 1 ,190     ,70.58,134.32,137.47
BEGIN DESCRIPTION:
189.713--d/s face golfcourse culvert; surveyed channel
END DESCRIPTION:
XS GIS Cut Line= 4
     3068143.859    13811498.055     3068034.781    13811584.674
     3067964.526    13811627.766     3067732.005    13811790.897
#Sta/Elev= 30
       0   69.75   65.58   68.39   78.86   68.26   89.54   68.48  103.89    68.3
  110.89   67.47  123.04   65.56  139.29   61.42  162.99   59.96  179.93    50.9
  180.22   45.43   199.4   45.62  200.27   51.24  217.38    60.2   221.7   60.37
  229.95   59.94  251.68   60.25  266.93   60.95  303.58   61.65  340.23    60.8
   348.6   61.18  358.55   61.17  391.67   61.97  413.52   62.02  434.75   61.68
  450.17   61.78  456.29   62.01  467.05   62.93  488.59   62.62  505.74   63.38
#Mann= 3 , 0 , 0
       0      .1       0  162.99    .015       0  217.38     .08       0
#XS Ineff= 2 , 0
       0     163             218       0
Permanent Ineff=
       T       T
Bank Sta=162.99,217.38
XS Rating Curve= 0
Exp/Cntr=.5,.3

Type RM Length L Ch R = 1 ,55      ,19.67,55.4,17.92
BEGIN DESCRIPTION:
55.396--d/s exit golfcourse culvert; channel adjusted from survey XS 190
END DESCRIPTION:
XS GIS Cut Line= 3
     3068024.516    13811506.765     3067927.679    13811493.607
     3067725.417    13811655.092
#Sta/Elev= 30
       0   65.12    8.86   65.06   19.54   65.28   30.22      65   33.89    65.1
   40.89   64.27   53.04   62.36   69.29   58.22   92.99   56.76  109.93    47.7
  110.22   42.23   129.4   42.42  130.27   48.04  147.38      57   151.7   57.17
  160.29   56.75  176.09   58.74  186.01   59.06  196.68   60.52  200.13   60.79
  224.17    61.8  239.37   61.74  251.51   61.03  260.72   61.24  282.07   61.05
   296.3   61.57  314.08   61.68  324.76   62.52  335.43   62.93  356.55   63.22
#Mann= 3 , 0 , 0
       0      .1       0   92.99    .015       0  147.38     .08       0
#XS Ineff= 2 , 0
       0      30             351       0
Permanent Ineff=
       T       T
Bank Sta=92.99,147.38
XS Rating Curve= 0
Exp/Cntr=.3,.1

Chan Stop Cuts=-1